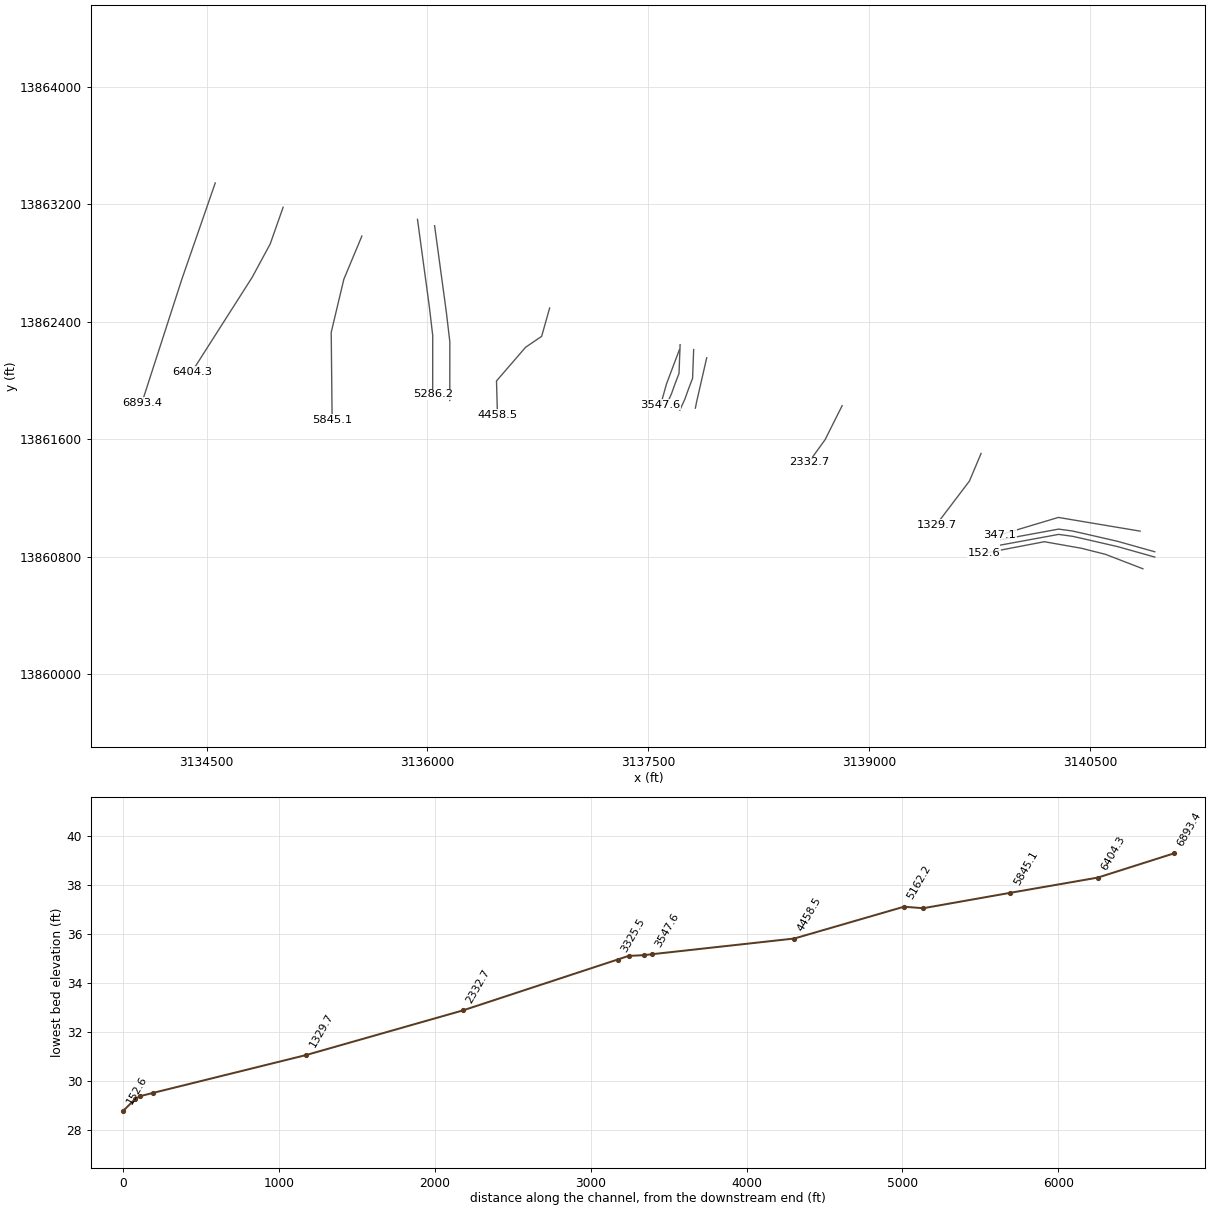
--- H118-00-00.PRJ (project) ---

Proj Title=H118-00-00
Current Plan=p03
Default Exp/Contr=.3,.1
English Units
Geom File=g01
Flow File=f01
Flow File=f03
Plan File=p01
Plan File=p03
Y Axis Title=Elevation
X Axis Title(PF)=Main Channel Distance
X Axis Title(XS)=Station
BEGIN DESCRIPTION:
Hunting Bayou Watershed
Tributary 12.05 to Hunting Bayou
HCFCD Unit H118-00-00
Flood Hazard Model
10, 2, 1, 0.2% Event
Filename H118-00-00.prj
Prepared by:  Watershed Concepts  Date: 06/04/02
Reviewed by:                      Date:
STATUS FINAL
END DESCRIPTION:
DSS Export Rating Curves= 0
DSS Export Rating Curve Sorted= 0
DSS Export Volume Flow Curves= 0
DXF OffsetX= 0
DXF OffsetY= 0
DXF ScaleX= 1
DXF ScaleY= 10

--- H118-00-00.p03 (plan) ---

Plan Title=Floodway
Version=Version 3.0.1  Mar 2001
Short Identifier=Floodway0607
Geom File=g01
Flow File=f03
Subcritical Flow
K Sum by GR= 0
Std Step Tol= 0.01
Critical Tol= 0.01
Num of Std Step Trials= 20
Max Error Tol= 0.3
Flow Tol Ratio= 0.001
Split Flow NTrial= 30
Split Flow Tol= 0.02
Split Flow Ratio= 0.02
Log Output Level= 0
Friction Slope Method= 1
Unsteady Friction Slope Method= 2
Parabolic Critical Depth
Global Vel Dist= 0 , 0 , 0
Global Log Level= 0
CheckData=True
Encroach Param=-1 ,0,0, 2
Encroach River=H118-00-00
Encroach Reach=Reach - 1
Encroach Node=6893.4
       1  4979.7  5015.8
Encroach Node=6404.3
       1  4979.7  5015.8
Encroach Node=5845.1
       1  4979.7  5015.8
Encroach Node=5286.2
       1    4980    5025
Encroach Node=5224.2
       1    4980    5025
Encroach Node=5162.2
       1    4980    5025
Encroach Node=4458.5
       1    4980    5020
Encroach Node=3547.6
       1    4980    5020
Encroach Node=3494.0
       1    4980    5065
Encroach Node=3445.0
       1    4980    5065
Encroach Node=3396.0
       1    4980    5065
Encroach Node=3325.5
       1    4975    5050
Encroach Node=2332.7
       1  4973.8    5030
Encroach Node=1329.7
       1  4966.4    5030
Encroach Node=347.1
       1  4977.4    5030
Encroach Node=264.3
       1    4975    5025
Encroach Node=246.3
       1    4975    5025
Encroach Node=228.3
       1    4975    5025
Encroach Node=152.6
       1    4978    5029
Encroach Reach=H118-00-00_0002
Encroach Node=6893.4
       1  4979.7  5015.8
Encroach Node=6404.3
       1  4979.7  5015.8
Encroach Node=5845.1
       1  4979.7  5015.8
Encroach Node=5286.2
       1    4980    5025
Encroach Node=5224.2
       1    4980    5025
Encroach Node=5162.2
       1    4980    5025
Encroach Node=4458.5
       1    4980    5020
Encroach Node=3547.6
       1    4980    5020
Encroach Node=3494.0
       1    4980    5065
Encroach Node=3445.0
       1    4980    5065
Encroach Node=3396.0
       1    4980    5065
Encroach Node=3325.5
       1    4975    5050
Encroach Node=2332.7
       1  4973.8    5030
Encroach Node=1329.7
       1  4966.4    5030
Encroach Node=347.1
       1  4977.4    5030
Encroach Node=264.3
       1    4975    5025
Encroach Node=246.3
       1    4975    5025
Encroach Node=228.3
       1    4975    5025
Encroach Node=152.6
       1    4978    5029
Computation Interval=1HOUR
Output Interval=1HOUR
Run HTab= 0
Run UNet= 0
Run PostProcess= 0
UNET Theta= 1
UNET ZTol= 0.02
UNET ZSATol= 0.1
UNET MxIter= 20
UNET MaxInSteps= 20
UNET DtIC= 0
UNET DtMin= 0
UNET MaxCRTS= 20
UNET WFStab= 2
UNET SFStab= 1
UNET WFX= 1
UNET SFX= 1
UNET Convert EG Bridges=-1
UNET Use Existing IB Tables=-1
Instantaneous Interval=1HOUR
Write IC File= 0
Write Velocity= 0
Write Detailed= 0

--- H118-00-00.p01 (plan) ---

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Plan Title=FEMA Effective June 2007
Short Identifier=FEMAeff0607
Geom File=g01
Flow File=f01
Encroach Param=-1 ,0,0, 0

--- H118-00-00.f03 (steady flow) ---

Flow Title= Floodway
Number of Profiles= 2
Profile Names=1PCT_100yr, 1PCTFloodway_100yrFW
River Rch & RM=H118-00-00,H118-00-00_0002,6893.4
     707     707
River Rch & RM=H118-00-00,H118-00-00_0002,5286.2
     920     920
River Rch & RM=H118-00-00,H118-00-00_0002,4458.5
    1040    1040
River Rch & RM=H118-00-00,H118-00-00_0002,3494
    1222    1222
River Rch & RM=H118-00-00,H118-00-00_0002,2332.7
    1404    1404
River Rch & RM=H118-00-00,H118-00-00_0002,1329.7
    1576    1576
River Rch & RM=H118-00-00,H118-00-00_0002,347.1
    1765    1765
Boundary for River Rch & Prof#=H118-00-00,H118-00-00_0002, 1
Up Type= 0
Dn Type= 3
Dn Slope= 0.00160
Boundary for River Rch & Prof#=H118-00-00,H118-00-00_0002, 2
Up Type= 0
Dn Type= 3
Dn Slope= 0.00160

--- H118-00-00.f01 (steady flow) ---

Flow Title= FEMA Effective June 2007
Number of Profiles= 4
Profile Names=10PCT_10yr, 2PCT_50yr, 1PCT_100yr, 0.2PCT_500yr
River Rch & RM=H118-00-00,H118-00-00_0002,6893.4
     379     591     707    1067
River Rch & RM=H118-00-00,H118-00-00_0002,5286.2
     496     773     920    1366
River Rch & RM=H118-00-00,H118-00-00_0002,4458.5
     563     875    1040    1535
River Rch & RM=H118-00-00,H118-00-00_0002,3494
     664    1030    1222    1791
River Rch & RM=H118-00-00,H118-00-00_0002,2332.7
     764    1186    1404    2047
River Rch & RM=H118-00-00,H118-00-00_0002,1329.7
     859    1332    1576    2289
River Rch & RM=H118-00-00,H118-00-00_0002,347.1
     964    1493    1765    2554
Boundary for River Rch & Prof#=H118-00-00,H118-00-00_0002, 1
Up Type= 0
Dn Type= 3
Dn Slope= 0.00160
Boundary for River Rch & Prof#=H118-00-00,H118-00-00_0002, 2
Up Type= 0
Dn Type= 3
Dn Slope= 0.00160
Boundary for River Rch & Prof#=H118-00-00,H118-00-00_0002, 3
Up Type= 0
Dn Type= 3
Dn Slope= 0.00160
Boundary for River Rch & Prof#=H118-00-00,H118-00-00_0002, 4
Up Type= 0
Dn Type= 3
Dn Slope= 0.00160

--- H118-00-00.g01 (geometry) ---

Geom Title=H118-00-00 June 2007

River Reach=H118-00-00,H118-00-00_0002
Reach XY= 13
      3134500.83     13863175.65      3135241.29     13862900.97
       3136071.5        13862593      3137742.75        13861986
      3138218.32     13861792.57       3138303.1     13861809.53
      3138401.75        13861860      3138438.75        13861867
      3138472.75        13861859       3140002.5        13861303
      3140569.75        13861098      3140570.11     13860894.06

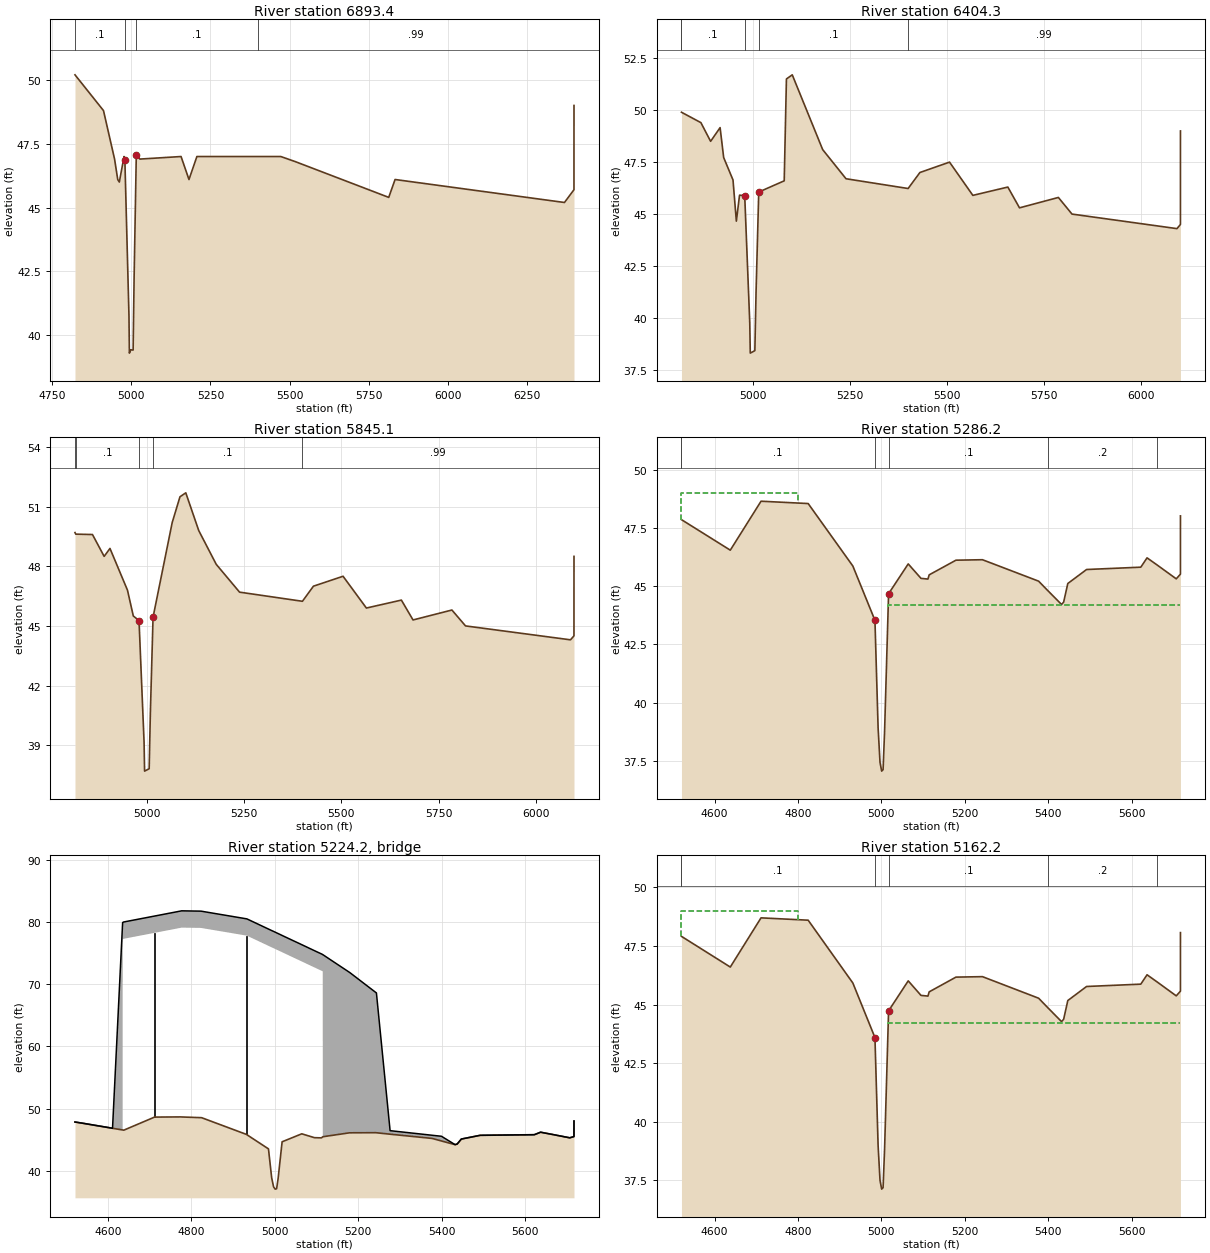
Type RM Length L Ch R = 1 ,6893.4,489.5,489.1,382
XS GIS Cut Line= 3
      3134558.96     13863343.69      3134331.31     13862686.04
      3134060.99     13861848.51
BEGIN DESCRIPTION:
Cross Section 6893.4 - Interpolated
END DESCRIPTION:
#Sta/Elev= 26
  4822.2    50.2  4912.2    48.8  4947.2    46.9  4957.2    46.1  4962.2      46
  4977.2      47  4979.7   46.88  4992.7   40.76    4994    39.3  4998.4   39.43
  5005.8   39.42  5007.3   40.81  5008.9   42.25  5015.8   47.05  5027.2    46.9
  5157.2      47  5182.2    46.1  5207.2      47    5400      47  5472.2      47
  5518.1    46.8  5813.1    45.4  5833.1    46.1  6368.1    45.2  6398.1    45.7
  6398.2      49
#Mann= 4 , 1 , 0
 4822.20     0.1       0  4979.7    0.04       0  5015.8     0.1       0
    5400    0.99       0
Bank Sta=4979.70,5015.80
Exp/Cntr=0.3,0.1

Type RM Length L Ch R = 1 ,6404.3,526.4,559.2,810.9
XS GIS Cut Line= 4
      3135020.04     13863178.19      3134932.53     13862929.12
      3134810.46     13862702.42      3134401.31     13862059.56
BEGIN DESCRIPTION:
Cross Section 6404.3
END DESCRIPTION:
#Sta/Elev= 30
    4817    49.9    4867    49.4    4892    48.5  4916.4   49.16  4925.6   47.72
  4949.6   46.64  4958.2   44.66  4966.4   45.91  4979.7   45.89  4992.7   39.77
    4994   38.31  5005.8   38.43  5008.9   41.26  5015.8   46.06  5081.3    46.6
    5087    51.5    5102    51.7  5180.3    48.1  5240.3    46.7    5400   46.23
  5430.3      47  5506.5    47.5  5566.5    45.9  5656.5    46.3  5686.5    45.3
  5786.5    45.8  5821.5      45  6091.5    44.3  6100.4    44.5  6100.5      49
#Mann= 5 , 1 , 0
 4817.00     0.2       0    4817     0.1       0  4979.7    0.04       0
  5015.8     0.1       0    5400    0.99       0
Bank Sta=4979.70,5015.80
Exp/Cntr=0.3,0.1

Type RM Length L Ch R = 1 ,5845.1,562.9,558.9,548.7
XS GIS Cut Line= 4
      3135554.80     13862981.82      3135432.37     13862687.98
      3135346.66     13862326.80      3135352.78     13861732.99
BEGIN DESCRIPTION:
Cross Section 5845.1 - Interpolated
END DESCRIPTION:
#Sta/Elev= 30
    4815    49.7    4817   49.62    4860    49.6    4890    48.5    4905    48.9
    4950    46.8    4965    45.5  4979.7   45.27  4992.7   39.15    4994   37.69
  5005.8   37.81  5008.9   40.64  5015.8   45.44    5065    50.2    5085    51.5
    5100    51.7  5133.3    49.8  5178.3    48.1  5238.3    46.7    5400   46.24
  5428.3      47  5504.5    47.5  5564.5    45.9  5654.5    46.3  5684.5    45.3
  5784.5    45.8  5819.5      45  6089.5    44.3  6098.4    44.5  6098.5    48.5
#Mann= 5 , 1 , 0
 4815.00     0.2       0    4817     0.1       0  4979.7    0.04       0
  5015.8     0.1       0    5400    0.99       0
Bank Sta=4979.70,5015.80
Exp/Cntr=0.5,0.3

Type RM Length L Ch R = 1 ,5286.2,124,124,124
XS GIS Cut Line= 4
      3135932.60     13863095.65      3136012.56     13862505.58
      3136036.14     13862305.13      3136035.72     13861905.98
BEGIN DESCRIPTION:
Upstream Section of Bridge/Culvert/Weir
END DESCRIPTION:
#Sta/Elev= 30
  4520.7   47.85  4637.8   46.54  4711.5   48.64  4824.5   48.54  4931.6   45.86
  4984.6   43.53  4992.2   38.91  4996.8   37.43  5000.7   37.06  5004.1   37.12
  5007.7   38.76  5017.3   44.67  5064.4   45.95    5095   45.33  5111.7    45.3
  5114.6   45.48  5178.8   46.11  5242.4   46.13    5377   45.21  5399.3    44.8
    5432   44.21    5437   44.31    5447   45.11    5492   45.71    5622   45.81
    5637   46.21  5660.7   45.91    5707   45.31    5717   45.51  5717.1   48.01
#Mann= 6 , 1 , 0
 4520.70     0.2       0  4520.7     0.1       0  4984.6    0.04       0
  5017.3     0.1       0  5399.3     0.2       0  5660.7    0.99       0
#XS Ineff= 2 , 0
       0    4800      49  5016.4       0    44.2
Bank Sta=4984.60,5017.30
Exp/Cntr=0.5,0.3

Type RM Length L Ch R = 3 ,5224.2,,,
BEGIN DESCRIPTION:
LOCKWOOD DRIVE
Structure ID: H18-5
END DESCRIPTION:
Bridge Culvert--1,0,-1,-1, 0
Deck Dist Width WeirC Skew NumUp NumDn MinLoCord MaxHiCord MaxSubmerge Is_Ogee
10,104,2.6,,50,50,,,0.95,0,1,1,,
  4520.7  4540.7  4610.7  4634.9 4635.01  4635.1  4635.2  4636.5  4637.8  4711.5
  4774.3  4776.4  4822.4  4824.5  4931.6    4933  4984.6  4992.2  4996.8  5000.7
  5004.1  5007.7  5017.3  5064.4    5095  5111.7  5114.5  5114.6 5114.69  5114.8
  5114.9  5115.9  5178.8  5179.1  5242.4  5242.9  5243.4  5276.2    5377  5399.3
    5432    5437    5447    5492    5622    5637  5660.7    5707    5717  5717.1
   47.84   47.63   46.84   79.88   79.89   79.89    79.9   79.98      80   80.95
   81.76   81.79   81.74   81.72   80.51   80.49   78.86   78.62   78.48   78.36
   78.25   78.14   77.83   76.35   75.38   74.86   74.77   74.77   74.76   74.76
   74.75    74.7    71.9   71.89   68.64   68.62   68.59   46.45   45.71   45.55
    44.2    44.3    45.1    45.7    45.8    46.2    45.9    45.3    45.5      48
   47.84   47.62   46.83   46.56   46.56   77.19    77.2   77.28    77.3   78.25
   79.06   79.09   79.04   79.02   77.81   77.79   76.16   75.92   75.78   75.66
   75.55   75.44   75.13   73.65   72.68   72.16   72.07   72.07   72.06   45.47
   45.47   45.48    46.1    46.1   46.12   46.11   46.11   45.88    45.2   44.79
    44.2    44.3    45.1    45.7    45.8    46.2    45.9    45.3    45.5      48
  4520.7  4540.7  4610.7  4634.9 4635.01  4635.1  4635.2  4636.5  4637.8  4711.5
  4774.3  4776.4  4822.4  4824.5  4931.6    4933  4984.6  4992.2  4996.8  5000.7
  5004.1  5007.7  5017.3  5064.4    5095  5111.7  5114.5  5114.6 5114.69  5114.8
  5114.9  5115.9  5178.8  5179.1  5242.4  5242.9  5243.4  5276.2    5377  5399.3
    5432    5437    5447    5492    5622    5637  5660.7    5707    5717  5717.1
   47.93   47.71   46.92   79.88   79.89   79.89    79.9   79.98      80   80.95
   81.76   81.79   81.74   81.72   80.51   80.49   78.86   78.62   78.48   78.36
   78.25   78.14   77.83   76.35   75.38   74.86   74.77   74.77   74.76   74.76
   74.75    74.7    71.9   71.89   68.64   68.62   68.59   46.45   45.71   45.55
   44.29   44.39   45.19   45.79   45.89   46.29   45.99   45.39   45.59   48.09
   47.93   47.71   46.92   46.65   46.65   77.28   77.29   77.37   77.39   78.34
   79.15   79.18   79.13   79.11    77.9   77.88   76.25   76.01   75.87   75.75
   75.64   75.53   75.22   73.74   72.77   72.25   72.16   72.16   72.15   45.56
   45.56   45.57   46.19   46.19   46.21    46.2    46.2   45.97   45.29   44.88
   44.29   44.39   45.19   45.79   45.89   46.29   45.99   45.39   45.59   48.09
Pier Skew, UpSta & Num, DnSta & Num=,4711.5, 2 ,4711.5, 2 , 0 , 0 , 0 ,,
       4       4
   47.57   79.28
       4       4
   47.66   79.37
Pier Skew, UpSta & Num, DnSta & Num=,4931.6, 2 ,4931.6, 2 , 0 , 0 , 0 ,,
       4       4
   44.76   78.83
       4       4
   44.85   78.92
BR Coef= 1 , 1 , 0 ,1.25, 0 ,,,0.8,0,2,0,
Wspro=,,,, 1 ,,,, 0 ,,,, 0 ,,,,-1 ,-1 ,-1 , 0 , 0 , 0 , 0 , 0
BC Design=,, 0 ,, 0 ,,,,,,
BR U #Sta/Elev= 50
  4520.7   47.84  4540.7   47.62  4610.7   46.83  4634.9   46.56 4635.01   46.56
  4635.1   46.56  4635.2   46.56  4636.5   46.54  4637.8   46.53  4711.5   48.63
  4774.3   48.66  4776.4   48.65  4822.4   48.54  4824.5   48.53  4931.6   45.85
    4933   45.79  4984.6   43.52  4992.2    38.9  4996.8   37.42  5000.7   37.05
  5004.1   37.11  5007.7   38.75  5017.3   44.66  5064.4   45.94    5095   45.32
  5111.7   45.29  5114.5   45.46  5114.6   45.47 5114.69   45.47  5114.8   45.47
  5114.9   45.47  5115.9   45.48  5178.8    46.1  5179.1    46.1  5242.4   46.12
  5242.9   46.11  5243.4   46.11  5276.2   45.88    5377    45.2  5399.3   44.79
    5432    44.2    5437    44.3    5447    45.1    5492    45.7    5622    45.8
    5637    46.2  5660.7    45.9    5707    45.3    5717    45.5  5717.1      48
BR U #Mann= 6
 4520.70     0.2  4520.7     0.1  4984.6    0.04  5017.3     0.1  5399.3     0.2
  5660.7    0.99
BR U Banks=4984.60,5017.30
BR D #Sta/Elev= 50
  4520.7   47.93  4540.7   47.71  4610.7   46.92  4634.9   46.65 4635.01   46.65
  4635.1   46.65  4635.2   46.65  4636.5   46.63  4637.8   46.62  4711.5   48.72
  4774.3   48.75  4776.4   48.74  4822.4   48.63  4824.5   48.62  4931.6   45.94
    4933   45.88  4984.6   43.61  4992.2   38.99  4996.8   37.51  5000.7   37.14
  5004.1    37.2  5007.7   38.84  5017.3   44.75  5064.4   46.03    5095   45.41
  5111.7   45.38  5114.5   45.55  5114.6   45.56 5114.69   45.56  5114.8   45.56
  5114.9   45.56  5115.9   45.57  5178.8   46.19  5179.1   46.19  5242.4   46.21
  5242.9    46.2  5243.4    46.2  5276.2   45.97    5377   45.29  5399.3   44.88
    5432   44.29    5437   44.39    5447   45.19    5492   45.79    5622   45.89
    5637   46.29  5660.7   45.99    5707   45.39    5717   45.59  5717.1   48.09
BR D #Mann= 6
 4520.70     0.2  4520.7     0.1  4984.6    0.04  5017.3     0.1  5399.3     0.2
  5660.7    0.99
BR D Banks=4984.60,5017.30

Type RM Length L Ch R = 1 ,5162.2,703.7,703.7,703.7
XS GIS Cut Line= 4
      3136048.86     13863052.53      3136128.82     13862462.46
      3136152.40     13862262.01      3136151.98     13861862.86
BEGIN DESCRIPTION:
Downstream Section of Bridge/Culvert/Weir
END DESCRIPTION:
#Sta/Elev= 30
  4520.7   47.91  4637.8    46.6  4711.5    48.7  4824.5    48.6  4931.6   45.92
  4984.6   43.59  4992.2   38.97  4996.8   37.49  5000.7   37.12  5004.1   37.18
  5007.7   38.82  5017.3   44.73  5064.4   46.01    5095   45.39  5111.7   45.36
  5114.6   45.54  5178.8   46.17  5242.4   46.19    5377   45.27  5399.3   44.86
    5432   44.27    5437   44.37    5447   45.17    5492   45.77    5622   45.87
    5637   46.27  5660.7   45.97    5707   45.37    5717   45.57  5717.1   48.07
#Mann= 6 , 1 , 0
 4520.70     0.2       0  4520.7     0.1       0  4984.6    0.04       0
  5017.3     0.1       0  5399.3     0.2       0  5660.7    0.99       0
#XS Ineff= 2 , 0
       0    4800      49  5016.4       0    44.2
Bank Sta=4984.60,5017.30
Exp/Cntr=0.5,0.3

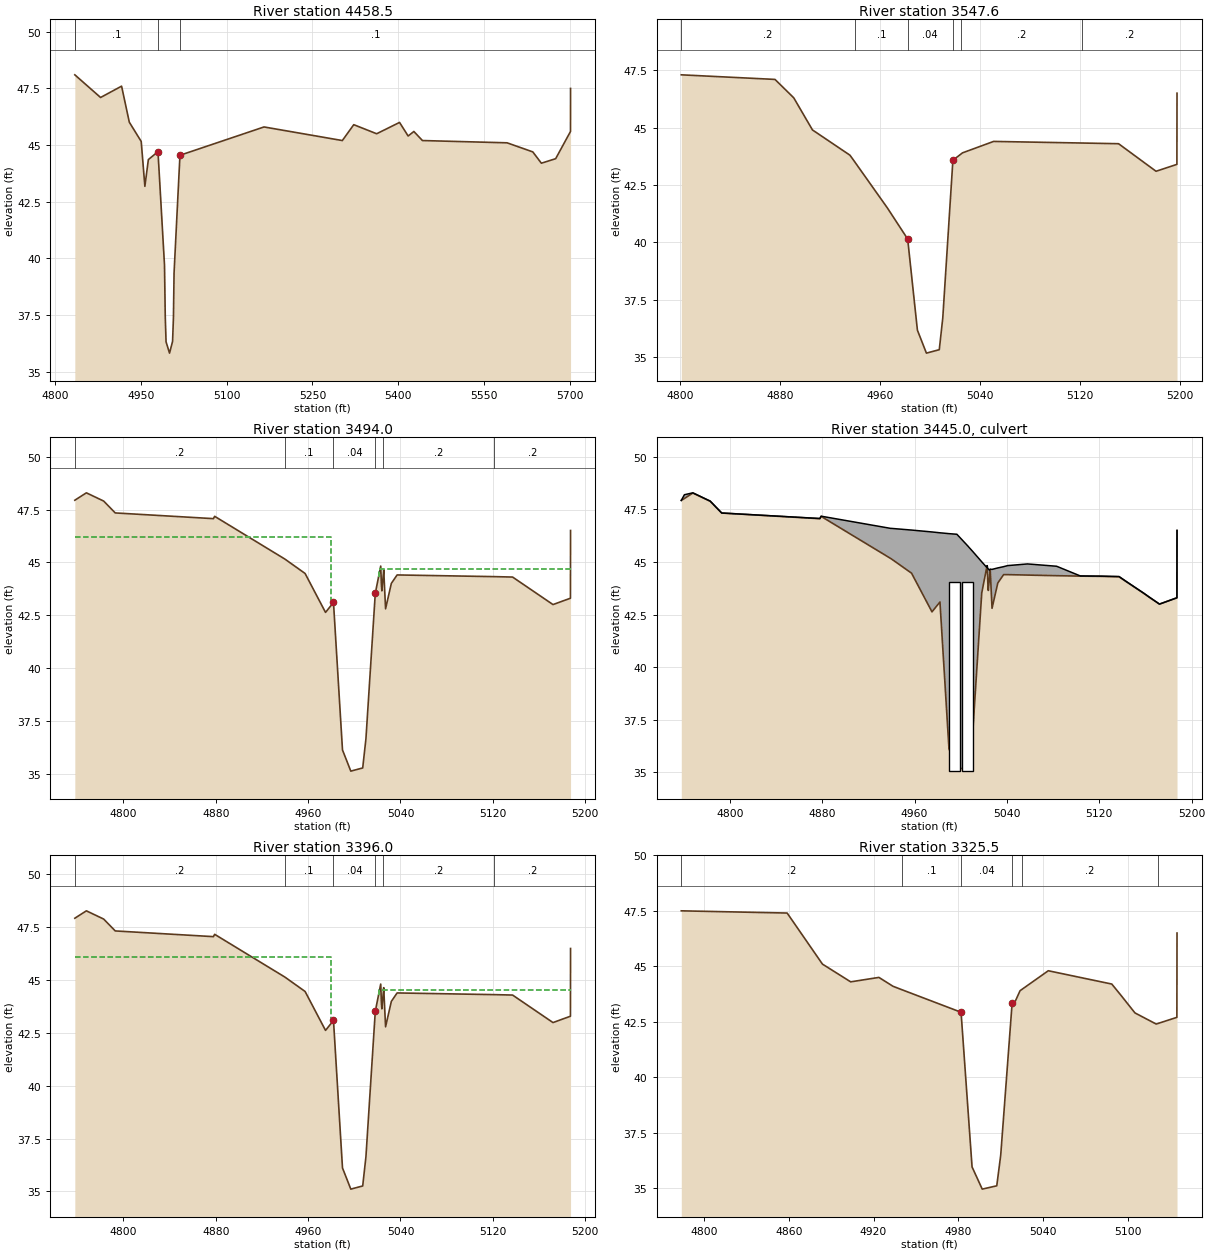
Type RM Length L Ch R = 1 ,4458.5,910.6,910.9,1011.9
XS GIS Cut Line= 5
      3136830.34     13862492.54      3136775.89     13862299.49
      3136666.99     13862225.24      3136469.28     13861995.90
      3136475.75     13861765.07
BEGIN DESCRIPTION:
Cross Section 4458.5
END DESCRIPTION:
#Sta/Elev= 30
  4834.9    48.1  4879.9    47.1  4916.6    47.6  4930.1   46.01  4950.9   45.16
  4957.3   43.18  4963.4   44.36  4980.2   44.71  4991.6    39.7  4992.9   37.45
  4994.3   36.32  5000.4   35.82  5005.7   36.34  5007.2   37.38  5008.3   39.36
  5018.6   44.55  5165.5    45.8  5302.3    45.2  5322.3    45.9  5362.3    45.5
  5402.3      46  5417.3    45.4  5427.3    45.6  5442.3    45.2  5590.1    45.1
  5635.1    44.7  5650.1    44.2  5675.1    44.4    5701    45.6  5701.1    47.5
#Mann= 4 , 1 , 0
 4834.90     0.2       0  4834.9     0.1       0  4980.2    0.04       0
  5018.6     0.1       0
Bank Sta=4980.20,5018.60
Exp/Cntr=0.3,0.1

Type RM Length L Ch R = 1 ,3547.6,32.7,53.6,35
XS GIS Cut Line= 3
      3137711.80     13862209.15      3137623.76     13861975.15
      3137584.38     13861833.82
BEGIN DESCRIPTION:
Cross Section 3547.6 - Interpolated
END DESCRIPTION:
#Sta/Elev= 21
  4800.8    47.3  4875.8    47.1  4890.8    46.3  4905.8    44.9  4935.8    43.8
  4939.9   43.49  4965.8    41.5    4982   40.15  4989.8   36.18    4997   35.18
  5007.3   35.33  5010.1   36.71  5018.2   43.58  5024.9   43.86  5025.8    43.9
  5050.8    44.4  5121.3   44.33  5150.8    44.3  5180.8    43.1  5197.5    43.4
  5197.6    46.5
#Mann= 6 , 1 , 0
 4800.80     0.2       0  4939.9     0.1       0    4982    0.04       0
  5018.2     0.1       0  5024.9     0.2       0  5121.3     0.2       0
Bank Sta=4982.00,5018.20
Exp/Cntr=0.5,0.3

Type RM Length L Ch R = 1 ,3494.0,98,98,98
XS GIS Cut Line= 5
      3137716.36     13862243.02      3137709.12     13862047.36
      3137680.81     13861973.44      3137657.19     13861907.01
      3137622.59     13861830.64
BEGIN DESCRIPTION:
Upstream Section of Bridge/Culvert/Weir
END DESCRIPTION:
#Sta/Elev= 28
    4758   47.94    4768   48.29    4783    47.9    4793   47.34    4878   47.07
  4879.1   47.18  4939.9   45.16  4957.4   44.48  4975.1   42.64    4982   43.11
  4989.8   36.14    4997   35.14  5007.3   35.29  5010.1   36.67  5018.2   43.54
  5022.9   44.83  5023.5   43.95  5023.9   43.66  5024.9   44.28  5025.5   44.66
  5027.1   42.81  5032.1   44.01  5037.1   44.41  5121.3   44.33  5137.1   44.31
  5172.1   43.01  5187.2   43.31  5187.3   46.51
#Mann= 6 , 1 , 0
 4758.00     0.2       0  4939.9     0.1       0    4982    0.04       0
  5018.2     0.1       0  5024.9     0.2       0  5121.3     0.2       0
#XS Ineff= 2 , 0
       0    4980    46.2    5021       0    44.7
Bank Sta=4982.00,5018.20
Exp/Cntr=0.5,0.3

Type RM Length L Ch R = 2 ,3445.0,,,
BEGIN DESCRIPTION:
ACCESS ROAD
Structure ID: H18-4
END DESCRIPTION:
Bridge Culvert--1,0,-1,-1, 0
Deck Dist Width WeirC Skew NumUp NumDn MinLoCord MaxHiCord MaxSubmerge Is_Ogee
10,78,3,,47,47,,,0.95,0,1,1,,
    4758  4760.7    4768  4770.7  4779.1    4783    4793    4878  4879.1  4939.3
  4939.9  4957.4  4975.1    4982  4989.8  4996.7    4997  5006.2  5007.3  5010.1
  5018.2  5022.1  5022.6  5022.8  5022.9  5023.3  5023.5  5023.9  5024.7  5024.9
  5025.5  5027.1  5032.1  5037.1  5040.6  5057.8    5083  5103.5  5121.3  5128.5
  5137.1  5143.5  5158.5  5163.4  5172.1  5187.2  5187.3
   47.93    48.2   48.29   48.22      48    47.9   47.33   47.07   47.18    46.6
    46.6   46.52   46.43   46.39   46.35   46.32    46.3   45.76   45.69   45.52
   45.01   44.77   44.74   44.79   44.83    44.7   44.69   44.67   44.62   44.62
   44.66   44.65   44.72   44.78   44.83   44.91    44.8   44.34   44.33   44.32
   44.31   44.07   43.52   43.33      43    43.3    46.5
   47.93   48.02   48.28   48.21   47.99   47.89   47.33   47.06   47.17   45.17
   45.15   44.47   42.63    43.1   36.13   35.17   35.13   35.26   35.28   36.66
   43.53   44.63   44.74   44.78   44.82   44.23   43.94   43.65   44.15   44.27
   44.65    42.8      44    44.4    44.4   44.38   44.35   44.33   44.32   44.31
    44.3   44.06   43.51   43.32      43    43.3    46.5
    4758  4760.7    4768  4770.7  4779.1    4783    4793    4878  4879.1  4939.3
  4939.9  4957.4  4975.1    4982  4989.8  4996.7    4997  5006.2  5007.3  5010.1
  5018.2  5022.1  5022.6  5022.8  5022.9  5023.3  5023.5  5023.9  5024.7  5024.9
  5025.5  5027.1  5032.1  5037.1  5040.6  5057.8    5083  5103.5  5121.3  5128.5
  5137.1  5143.5  5158.5  5163.4  5172.1  5187.2  5187.3
   47.93    48.2   48.29   48.22      48    47.9   47.33   47.07   47.18    46.6
    46.6   46.52   46.43   46.39   46.35   46.32    46.3   45.76   45.69   45.52
   45.01   44.77   44.74   44.79   44.83    44.7   44.69   44.67   44.62   44.62
   44.66   44.65   44.72   44.78   44.83   44.91    44.8   44.34   44.33   44.32
   44.31   44.07   43.52   43.33      43    43.3    46.5
   47.93   48.02   48.28   48.21   47.99   47.89   47.33   47.06   47.17   45.17
   45.15   44.47   42.63    43.1   36.13   35.17   35.13   35.26   35.28   36.66
   43.53   44.63   44.74   44.78   44.82   44.23   43.94   43.65   44.15   44.27
   44.65    42.8      44    44.4    44.4   44.38   44.35   44.33   44.32   44.31
    44.3   44.06   43.51   43.32      43    43.3    46.5
BR Coef= 1 , 0 , 0 ,1.25, 0 ,,,0.8,-1,2,0,
Wspro=,,,, 1 ,,,, 0 ,,,, 0 ,,,,-1 ,-1 ,-1 , 0 , 0 , 0 , 0 , 0
Culvert=2,9.0,9.0,78.0,0.015,0.5,1.0,8,1,35.06,4994.50,35.13,4994.50,Culvert #1  ,0,10
Culvert=2,9.0,9.0,78.0,0.015,0.5,1.0,8,1,35.06,5006.00,35.13,5006.00,Culvert #2  ,0,10
BC Design=,, 0 ,, 0 ,,,,,,
BR U #Sta/Elev= 47
    4758   47.93  4760.7   48.02    4768   48.28  4770.7   48.21  4779.1   47.99
    4783   47.89    4793   47.33    4878   47.06  4879.1   47.17  4939.3   45.17
  4939.9   45.15  4957.4   44.47  4975.1   42.63    4982    43.1  4989.8   36.13
  4996.7   35.17    4997   35.13  5006.2   35.26  5007.3   35.28  5010.1   36.66
  5018.2   43.53  5022.1   44.63  5022.6   44.74  5022.8   44.78  5022.9   44.82
  5023.3   44.23  5023.5   43.94  5023.9   43.65  5024.7   44.15  5024.9   44.27
  5025.5   44.65  5027.1    42.8  5032.1      44  5037.1    44.4  5040.6    44.4
  5057.8   44.38    5083   44.35  5103.5   44.33  5121.3   44.32  5128.5   44.31
  5137.1    44.3  5143.5   44.06  5158.5   43.51  5163.4   43.32  5172.1      43
  5187.2    43.3  5187.3    46.5
BR U #Mann= 6
 4758.00     0.2  4939.9     0.1    4982    0.04  5018.2     0.1  5024.9     0.2
  5121.3     0.2
BR U Banks=4982.00,5018.20
BR D #Sta/Elev= 47
    4758   47.93  4760.7   48.02    4768   48.28  4770.7   48.21  4779.1   47.99
    4783   47.89    4793   47.33    4878   47.06  4879.1   47.17  4939.3   45.17
  4939.9   45.15  4957.4   44.47  4975.1   42.63    4982    43.1  4989.8   36.13
  4996.7   35.17    4997   35.13  5006.2   35.26  5007.3   35.28  5010.1   36.66
  5018.2   43.53  5022.1   44.63  5022.6   44.74  5022.8   44.78  5022.9   44.82
  5023.3   44.23  5023.5   43.94  5023.9   43.65  5024.7   44.15  5024.9   44.27
  5025.5   44.65  5027.1    42.8  5032.1      44  5037.1    44.4  5040.6    44.4
  5057.8   44.38    5083   44.35  5103.5   44.33  5121.3   44.32  5128.5   44.31
  5137.1    44.3  5143.5   44.06  5158.5   43.51  5163.4   43.32  5172.1      43
  5187.2    43.3  5187.3    46.5
BR D #Mann= 6
 4758.00     0.2  4939.9     0.1    4982    0.04  5018.2     0.1  5024.9     0.2
  5121.3     0.2
BR D Banks=4982.00,5018.20

Type RM Length L Ch R = 1 ,3396.0,70.5,70.5,70.5
XS GIS Cut Line= 5
      3137808.48     13862209.57      3137801.24     13862013.90
      3137772.93     13861939.98      3137749.31     13861873.55
      3137714.70     13861797.19
BEGIN DESCRIPTION:
Downstream Section of Bridge/Culvert/Weir
END DESCRIPTION:
#Sta/Elev= 28
    4758   47.91    4768   48.26    4783   47.87    4793   47.31    4878   47.04
  4879.1   47.15  4939.9   45.13  4957.4   44.45  4975.1   42.61    4982   43.08
  4989.8   36.11    4997   35.11  5007.3   35.26  5010.1   36.64  5018.2   43.51
  5022.9    44.8  5023.5   43.92  5023.9   43.63  5024.9   44.25  5025.5   44.63
  5027.1   42.78  5032.1   43.98  5037.1   44.38  5121.3    44.3  5137.1   44.28
  5172.1   42.98  5187.2   43.28  5187.3   46.48
#Mann= 6 , 1 , 0
 4758.00     0.2       0  4939.9     0.1       0    4982    0.04       0
  5018.2     0.1       0  5024.9     0.2       0  5121.3     0.2       0
#XS Ineff= 2 , 0
       0    4980    46.1    5021       0    44.5
Bank Sta=4982.00,5018.20
Exp/Cntr=0.5,0.3

Type RM Length L Ch R = 1 ,3325.5,987.8,992.8,931.5
XS GIS Cut Line= 3
      3137897.15     13862153.55      3137827.65     13861850.04
      3137820.25     13861811.04
BEGIN DESCRIPTION:
Cross Section 3325.5 - Interpolated
END DESCRIPTION:
#Sta/Elev= 24
  4783.8    47.5  4858.8    47.4  4883.8    45.1  4903.8    44.3  4923.8    44.5
  4933.8    44.1  4939.9   43.95    4982   42.93  4989.8   35.96    4997   34.96
  5007.3   35.11  5010.1   36.49  5018.2   43.36  5018.8    43.2  5023.8    43.9
  5024.9   43.95  5043.8    44.8  5088.8    44.2  5095.2    43.7  5105.2    42.9
  5120.2    42.4  5121.3   42.42  5134.9    42.7    5135    46.5
#Mann= 6 , 1 , 0
 4783.80     0.2       0  4939.9     0.1       0    4982    0.04       0
  5018.2     0.1       0  5024.9     0.2       0  5121.3     0.2       0
Bank Sta=4982.00,5018.20
Exp/Cntr=0.3,0.1

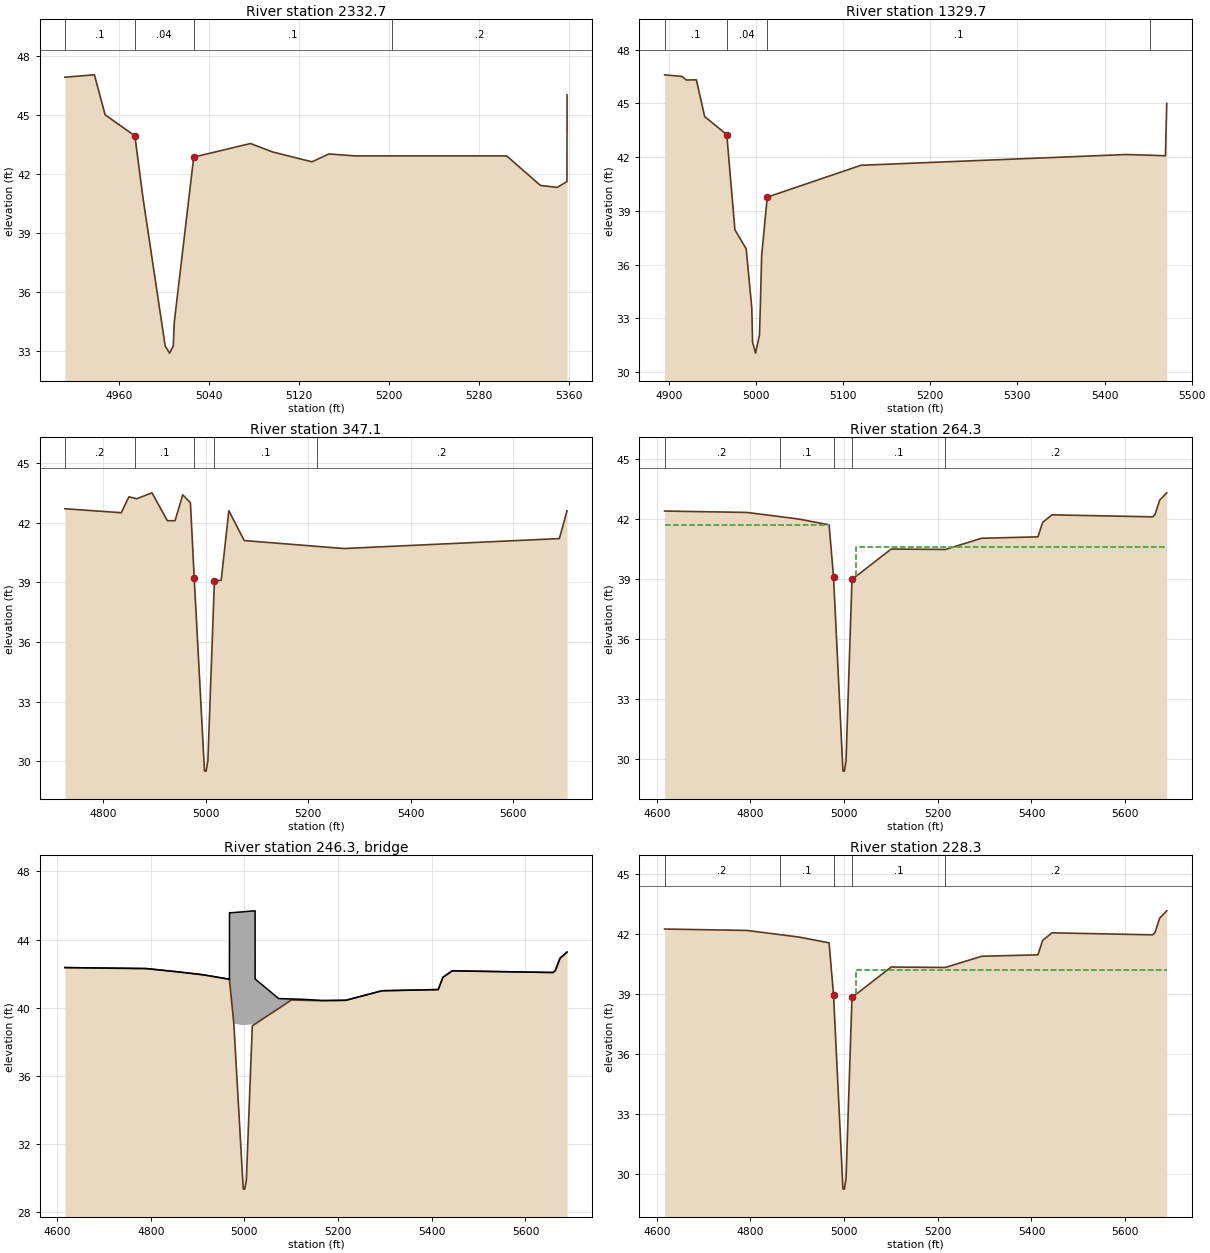
Type RM Length L Ch R = 1 ,2332.7,1000.7,1003,999.1
XS GIS Cut Line= 3
      3138816.90     13861827.46      3138701.31     13861596.29
      3138590.93     13861443.38
BEGIN DESCRIPTION:
Cross Section 2332.7
END DESCRIPTION:
#Sta/Elev= 21
  4911.5    46.9  4937.8   47.02  4947.3   44.99  4973.8   43.92  4981.1   40.74
  5000.8   33.24  5004.7   32.88    5008   33.24  5008.9   34.46  5026.2   42.84
  5076.7   43.53  5096.5    43.1  5131.5    42.6  5146.5      43  5169.9    42.9
  5202.8    42.9  5304.9    42.9  5334.9    41.4  5349.9    41.3  5358.5    41.6
  5358.6      46
#Mann= 4 , 1 , 0
 4911.50     0.1       0  4973.8    0.04       0  5026.2     0.1       0
  5202.8     0.2       0
Bank Sta=4973.80,5026.20
Exp/Cntr=0.3,0.1

Type RM Length L Ch R = 1 ,1329.7,1027.1,982.6,920.6
XS GIS Cut Line= 3
      3139760.74     13861502.45      3139681.57     13861314.43
      3139456.84     13861017.49
BEGIN DESCRIPTION:
Cross Section 1329.7
END DESCRIPTION:
#Sta/Elev= 20
    4895    46.6    4915   46.51    4920   46.31  4931.5   46.32    4941   44.27
  4966.4   43.26  4975.7   37.95  4988.7   36.88  4995.1   33.59    4996   31.68
  4999.4   31.06  5003.9   32.06  5004.9   33.67  5006.4   36.48  5012.8   39.77
  5120.5   41.55  5424.9   42.15  5452.5   42.11  5469.9   42.08  5471.4      45
#Mann= 4 , 1 , 0
 4895.00     0.1       0  4966.4    0.04       0  5012.8     0.1       0
  5452.5    0.99       0
Bank Sta=4966.40,5012.80
Exp/Cntr=0.3,0.1

Type RM Length L Ch R = 1 ,347.1,90.9,82.8,82.7
XS GIS Cut Line= 4
      3140841.10     13860973.60      3140450.33     13861039.14
      3140285.83     13861066.94      3139886.38     13860947.10
BEGIN DESCRIPTION:
Cross Section 347.1 - Interpolated
END DESCRIPTION:
#Sta/Elev= 23
    4725    42.7    4835    42.5    4850    43.3  4862.6   43.22    4865    43.2
    4895    43.5    4925    42.1    4940    42.1    4955    43.4    4970      43
  4977.4   39.22    4996   30.21  4997.5   29.52  5000.6   29.51  5004.1   30.04
  5016.8   39.09    5030    39.1    5045    42.6    5075    41.1  5216.2   40.81
  5270.1    40.7  5690.1    41.2  5705.1    42.6
#Mann= 5 , 1 , 0
 4725.00     0.2       0  4862.6     0.1       0  4977.4    0.04       0
  5016.8     0.1       0  5216.2     0.2       0
Bank Sta=4977.40,5016.80
Exp/Cntr=0.5,0.3

Type RM Length L Ch R = 1 ,264.3,36,36,36
XS GIS Cut Line= 6
      3140940.43     13860833.11      3140687.82     13860904.27
      3140465.17     13860955.58      3140382.21     13860974.28
      3140287.32     13860987.45      3139893.62     13860914.89
BEGIN DESCRIPTION:
Upstream Section of Bridge/Culvert/Weir
END DESCRIPTION:
#Sta/Elev= 19
  4616.7   42.38  4792.5   42.31  4903.1   41.98  4967.9   41.69  4977.4   39.09
  4997.5   29.39  5000.6   29.38  5004.1   29.91  5016.8   38.96  5100.4   40.48
  5216.3   40.46  5293.8   41.02  5413.8   41.09  5423.8   41.81  5443.8   42.19
  5658.8   42.09  5663.8   42.21  5673.8   42.93  5688.8   43.29
#Mann= 5 , 1 , 0
 4616.70     0.2       0  4862.6     0.1       0  4977.4    0.04       0
  5016.8     0.1       0  5216.2     0.2       0
#XS Ineff= 2 , 0
       0    4967    41.7    5026       0    40.6
Bank Sta=4977.40,5016.80
Exp/Cntr=0.5,0.3

Type RM Length L Ch R = 3 ,246.3,,,
BEGIN DESCRIPTION:
DIRT ROAD in RAIL YARD
Structure ID: H18-1
END DESCRIPTION:
Bridge Culvert--1,0,-1,-1, 0
Deck Dist Width WeirC Skew NumUp NumDn MinLoCord MaxHiCord MaxSubmerge Is_Ogee
10,16,2.6,,45,45,,,0.95,0,1,1,,
  4616.7  4790.7  4792.4  4792.5  4851.9  4855.8  4903.1    4914  4967.9 4967.99
  4968.1 4968.21  4972.2 4972.31  4972.4  4972.5  4977.4    4996  4997.5  5000.6
  5004.1  5016.8  5022.6 5022.66 5022.77 5022.88 5022.99  5023.1  5042.1  5073.1
  5100.4  5124.8  5164.5  5175.7    5216  5216.3  5221.9  5293.8  5413.8  5423.8
  5443.8  5658.8  5663.8  5673.8  5688.8
   42.36   42.31    42.3    42.3   42.13   42.12   41.97   41.93   41.68   41.66
   45.58   45.58   45.58   45.58   45.58   45.58   45.59   45.63   45.64   45.64
   45.65   45.68   45.69   45.69   45.69   41.69   41.69   41.68   41.25   40.54
   40.52    40.5   40.43   40.43   40.44   40.44   40.48      41   41.07   41.79
   42.17   42.07   42.19   42.91   43.27
   42.36   42.29   42.29   42.29   42.12   42.11   41.96   41.92   41.67   41.65
   41.62   41.59   40.49   40.46   40.44   40.41   39.07   38.98   38.99   38.99
      39   39.03   39.05   39.05   39.05   39.05   39.05   39.05    39.4   39.96
   40.46   40.44   40.42   40.42   40.44   40.44   40.48      41   41.07   41.79
   42.17   42.07   42.19   42.91   43.27
  4616.7  4790.7  4792.4  4792.5  4851.9  4855.8  4903.1    4914  4967.9 4967.99
  4968.1 4968.21  4972.2 4972.31  4972.4  4972.5  4977.4    4996  4997.5  5000.6
  5004.1  5016.8  5022.6 5022.66 5022.77 5022.88 5022.99  5023.1  5042.1  5073.1
  5100.4  5124.8  5164.5  5175.7    5216  5216.3  5221.9  5293.8  5413.8  5423.8
  5443.8  5658.8  5663.8  5673.8  5688.8
   42.36   42.31    42.3    42.3   42.13   42.12   41.97   41.93   41.68   41.66
   45.58   45.58   45.58   45.58   45.58   45.58   45.59   45.63   45.64   45.64
   45.65   45.68   45.69   45.69   45.69   41.69   41.69   41.68   41.25   40.54
   40.52    40.5   40.43   40.43   40.44   40.44   40.48      41   41.07   41.79
   42.17   42.07   42.19   42.91   43.27
    42.3   42.23   42.23   42.23   42.06   42.05    41.9   41.86   41.61   41.59
   41.56   41.53   40.43    40.4   40.38   40.35   39.01   38.92   38.93   38.93
   38.94   38.97   38.99   38.99   38.99   38.99   38.99   38.99   39.34    39.9
    40.4   40.38   40.36   40.36   40.38   40.38   40.42   40.94   41.01   41.73
   42.11   42.01   42.13   42.85   43.21
BR Coef= 1 , 1 , 0 ,1.25, 0 ,,,0.8,0,2,0,
Wspro=,,,, 1 ,,,, 0 ,,,, 0 ,,,,-1 ,-1 ,-1 , 0 , 0 , 0 , 0 , 0
BC Design=,, 0 ,, 0 ,,,,,,
BR U #Sta/Elev= 45
  4616.7   42.36  4790.7   42.29  4792.4   42.29  4792.5   42.29  4851.9   42.12
  4855.8   42.11  4903.1   41.96    4914   41.92  4967.9   41.67 4967.99   41.65
  4968.1   41.62 4968.21   41.59  4972.2   40.49 4972.31   40.46  4972.4   40.44
  4972.5   40.41  4977.4   39.07    4996   30.06  4997.5   29.37  5000.6   29.36
  5004.1   29.89  5016.8   38.94  5022.6   39.05 5022.66   39.05 5022.77   39.05
 5022.88   39.05 5022.99   39.05  5023.1   39.05  5042.1    39.4  5073.1   39.96
  5100.4   40.46  5124.8   40.44  5164.5   40.42  5175.7   40.42    5216   40.44
  5216.3   40.44  5221.9   40.48  5293.8      41  5413.8   41.07  5423.8   41.79
  5443.8   42.17  5658.8   42.07  5663.8   42.19  5673.8   42.91  5688.8   43.27
BR U #Mann= 5
 4616.70     0.2  4862.6     0.1  4977.4    0.04  5016.8     0.1  5216.2     0.2
BR U Banks=4977.40,5016.80
BR D #Sta/Elev= 45
  4616.7    42.3  4790.7   42.23  4792.4   42.23  4792.5   42.23  4851.9   42.06
  4855.8   42.05  4903.1    41.9    4914   41.86  4967.9   41.61 4967.99   41.59
  4968.1   41.56 4968.21   41.53  4972.2   40.43 4972.31    40.4  4972.4   40.38
  4972.5   40.35  4977.4   39.01    4996      30  4997.5   29.31  5000.6    29.3
  5004.1   29.83  5016.8   38.88  5022.6   38.99 5022.66   38.99 5022.77   38.99
 5022.88   38.99 5022.99   38.99  5023.1   38.99  5042.1   39.34  5073.1    39.9
  5100.4    40.4  5124.8   40.38  5164.5   40.36  5175.7   40.36    5216   40.38
  5216.3   40.38  5221.9   40.42  5293.8   40.94  5413.8   41.01  5423.8   41.73
  5443.8   42.11  5658.8   42.01  5663.8   42.13  5673.8   42.85  5688.8   43.21
BR D #Mann= 5
 4616.70     0.2  4862.6     0.1  4977.4    0.04  5016.8     0.1  5216.2     0.2
BR D Banks=4977.40,5016.80

Type RM Length L Ch R = 1 ,228.3,75.7,75.7,75.7
XS GIS Cut Line= 6
      3140940.49     13860797.11      3140687.88     13860868.27
      3140465.23     13860919.58      3140382.27     13860938.28
      3140287.38     13860951.45      3139893.68     13860878.89
BEGIN DESCRIPTION:
Downstream Section of Bridge/Culvert/Weir
END DESCRIPTION:
#Sta/Elev= 19
  4616.7   42.24  4792.5   42.17  4903.1   41.84  4967.9   41.55  4977.4   38.95
  4997.5   29.25  5000.6   29.24  5004.1   29.77  5016.8   38.82  5100.4   40.34
  5216.3   40.32  5293.8   40.88  5413.8   40.95  5423.8   41.67  5443.8   42.05
  5658.8   41.95  5663.8   42.07  5673.8   42.79  5688.8   43.15
#Mann= 5 , 1 , 0
 4616.70     0.2       0  4862.6     0.1       0  4977.4    0.04       0
  5016.8     0.1       0  5216.2     0.2       0
#XS Ineff= 2 , 0
       0    4967    41.5    5026       0    40.2
Bank Sta=4977.40,5016.80
Exp/Cntr=0.5,0.3

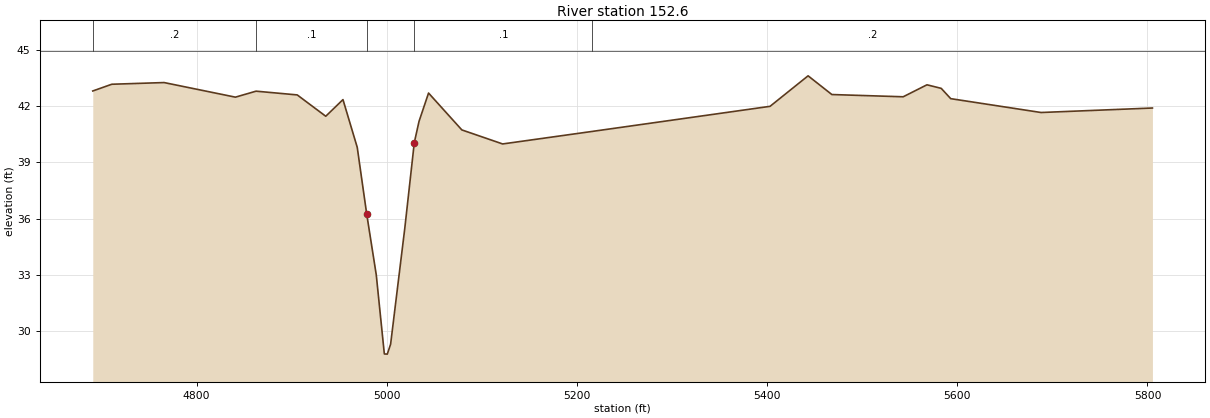
Type RM Length L Ch R = 1 ,152.6,0,0,0
XS GIS Cut Line= 5
      3140859.90     13860717.46      3140605.62     13860815.70
      3140442.84     13860856.84      3140190.63     13860901.56
      3139780.44     13860822.94
BEGIN DESCRIPTION:
Cross Section 152.6
END DESCRIPTION:
#Sta/Elev= 30
  4690.9   42.82  4710.9   43.18  4765.9   43.27  4840.9   42.49  4862.6   42.81
  4905.9   42.61  4935.9   41.47    4954   42.36    4969   39.81    4979   36.23
    4989      33  4997.5   28.77  5000.6   28.76  5004.1   29.29    5019   35.48
    5029   40.06    5034    41.2    5044   42.71    5079   40.74  5121.9   39.99
  5216.2   40.66  5403.1      42  5443.1   43.63  5468.1   42.63  5543.1   42.51
  5568.1   43.15  5583.1   42.96  5593.1   42.41  5688.1   41.67  5805.2   41.91
#Mann= 5 , 1 , 0
 4690.90     0.2       0  4862.6     0.1       0    4979    0.04       0
    5029     0.1       0  5216.2     0.2       0
Bank Sta=4979.00,5029.00
Exp/Cntr=0.3,0.1

Chan Stop Cuts=-1